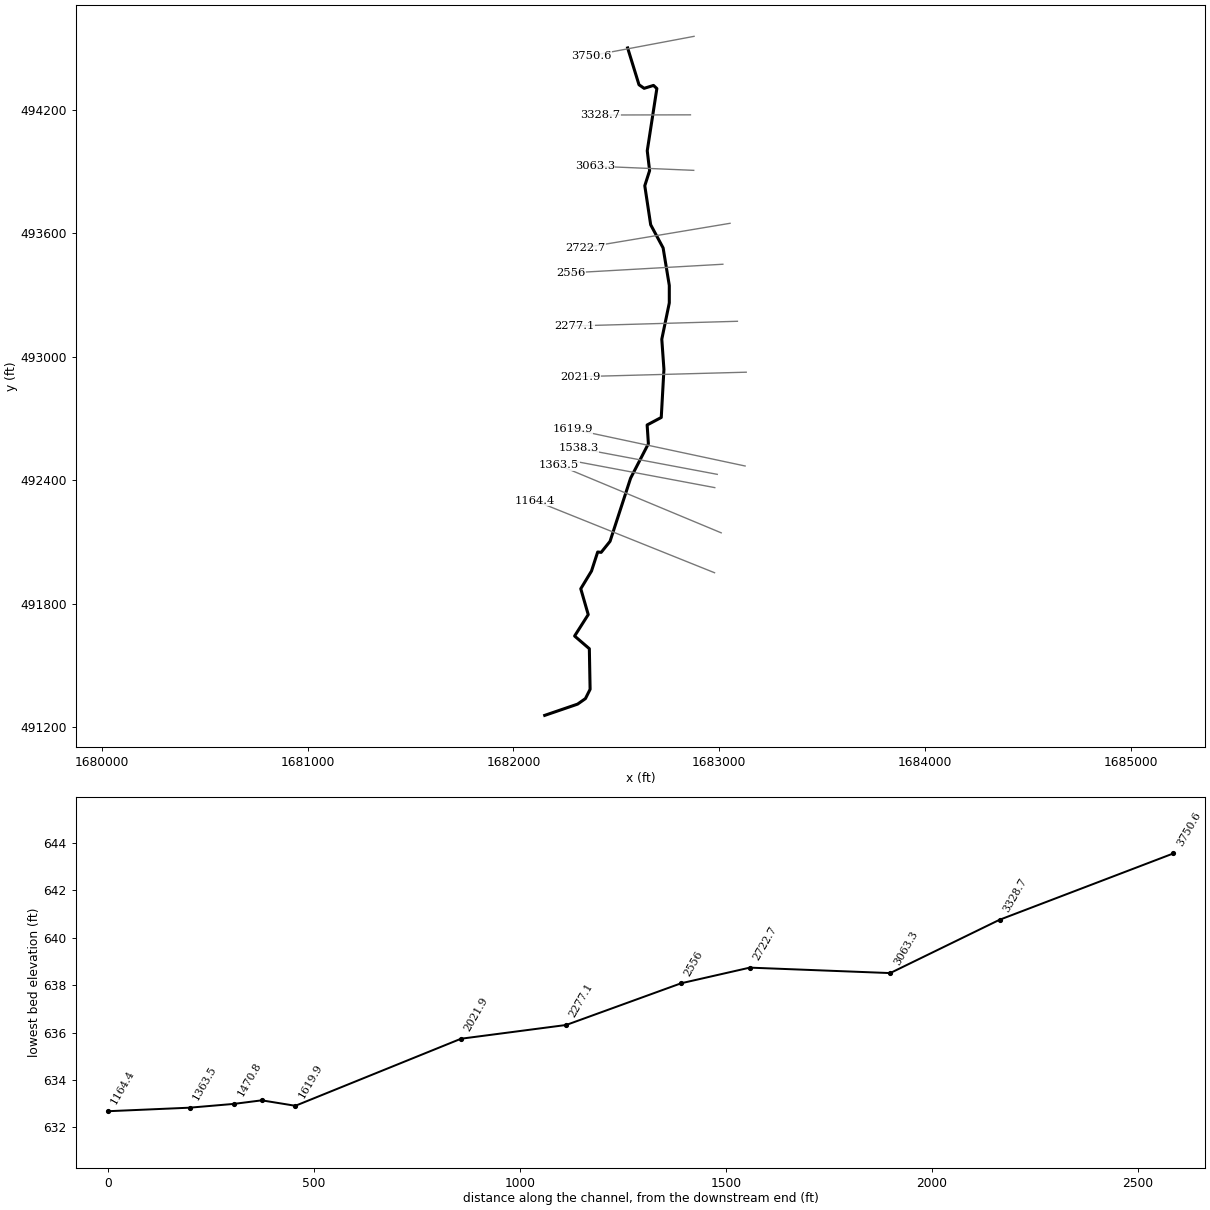
--- TraceCk.prj (project) ---

Proj Title=TraceCk
Current Plan=p01
Default Exp/Contr=0,0
English Units
Geom File=g01
Flow File=f01
Plan File=p01
BEGIN DESCRIPTION:
AMEC Environment & Infrastructure, 2013
Projection: NAD 1983 State Plane West Virginia South FIPS 4702 (US Feet)
Vertical Datum: NAVD 1988
END DESCRIPTION:
DSS Export Rating Curves= 0
DSS Export Rating Curve Sorted= 0
DSS Export Volume Flow Curves= 0
DXF OffsetX= 0
DXF OffsetY= 0
DXF ScaleX= 0
DXF ScaleY= 0

--- TraceCk.p01 (plan) ---

Plan Title=Floodplain
Program Version=4.00
Geom File=g01
Flow File=f01
K Sum by GR=0
Std Step Tol=0.01
Critical Tol=0.01
Num of Std Step Trials=20
Max Error Tol=0.3
Flow Tol Ratio=0.001
Split Flow NTrial=30
Split Flow Tol=0.02
Split Flow Ratio=0.02
Log Output Level=0
Friction Slope Method=1
Unsteady Friction Slope Method=2
Unsteady Bridges Friction Slope Method=1
Global Log Level=0
CheckData=False
Run HTab=0
Run UNet=0
Run PostProcess=0
UNET Theta=0
UNET Theta Warmup=0
UNET ZTol=0
UNET ZSATol=0
UNET MxIter=0
UNET MaxInSteps=0
UNET DtIC=0
UNET DtMin=0
UNET MaxCRTS=0
UNET WFStab=0
UNET SFStab=0
UNET WFX=0
UNET SFX=0
UNET DSS MLevel=0
UNET DZMax Abort=0
UNET Convert EG Bridges=0
UNET Use Existing IB Tables=0
UNET Froude Limit=0
UNET Froude Power=0
Write IC File=0
Echo Input=False
Echo Output=False
Write Detailed=0

--- TraceCk.f01 (steady flow) ---

Flow Title=USGS Regress. Eqn. (2010) - Western-Plateaus
Program Version=4.10
Number of Profiles= 1
Profile Names=P100yr
River Rch & RM=TraceCk,Main            ,3750.6
     633
River Rch & RM=TraceCk,Main            ,3328.7
     990
River Rch & RM=TraceCk,Main            ,2722.7
     998
River Rch & RM=TraceCk,Main            ,1619.9
    1016
Boundary for River Rch & Prof#=TraceCk,Main            , 1
Up Type= 0
Dn Type= 3
Dn Slope=0.0009
DSS Import GetInterval= 0
DSS Import GetPeak= 0
DSS Import FillOption= 0

--- TraceCk.g01 (geometry) ---

Geom Title=USGS 3m DEM
Program Version=4.10

River Reach=TraceCk         ,Main
Reach XY= 30
     1682555.235      494500.887     1682610.393       494322.05
     1682635.349      494304.689     1682680.922      494318.795
     1682697.198      494303.604     1682650.497      494001.173
     1682661.955      493904.819     1682638.518      493831.382
     1682667.163      493641.798      1682727.58      493529.298
     1682757.615      493347.007     1682757.615      493261.937
     1682721.156      493085.722     1682731.573      492939.021
     1682718.552      492705.514     1682649.976      492669.055
     1682656.052       492577.91     1682569.632       492410.64
     1682469.643       492103.52     1682426.588      492050.048
     1682409.697      492051.925     1682379.577      491959.189
     1682327.493      491873.251     1682363.724      491747.703
     1682297.535      491643.591     1682369.149      491581.959
     1682372.835      491384.773     1682350.265      491339.634
     1682312.071      491312.725     1682152.349      491258.037

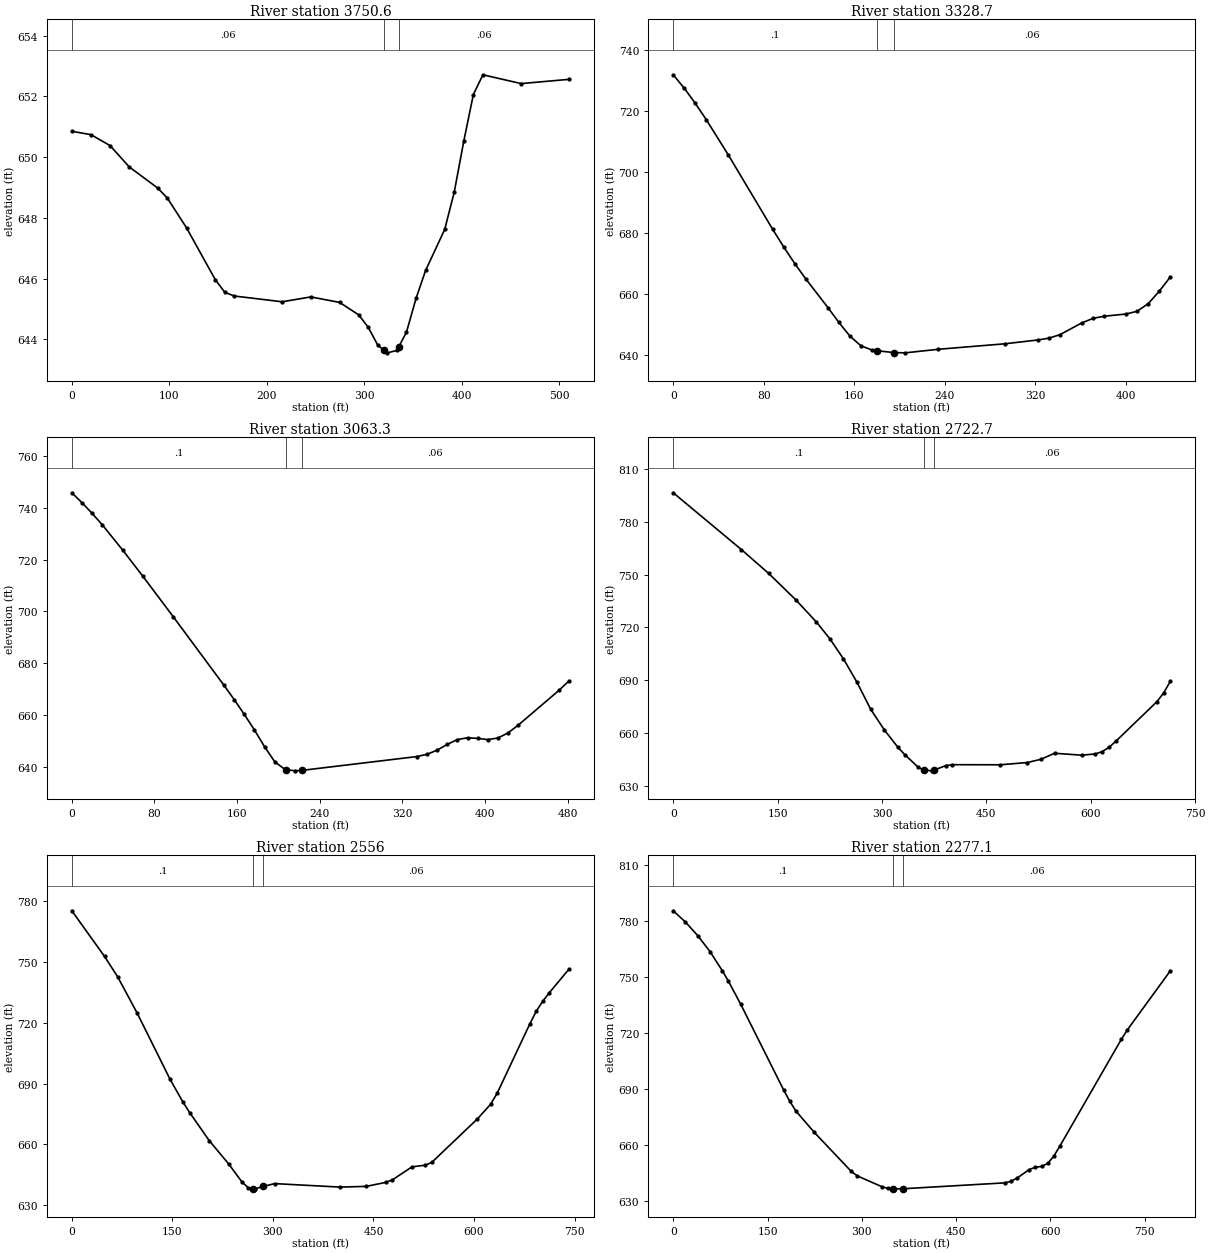
Type RM Length L Ch R = 1 ,3750.6  ,438.3,421.9,424.6
XS GIS Cut Line= 2
     1682878.061      494557.308     1682376.991      494462.992
#Sta/Elev= 30
       0  650.85    19.6  650.74    39.2  650.38    58.8  649.68    88.2  648.98
      98  648.65   117.7  647.67   147.1  645.97   156.9  645.55   166.7  645.43
   215.7  645.24   245.1   645.4   274.6  645.22   294.2  644.81     304   644.4
   313.8  643.81   320.3  643.64   323.6  643.56   333.4  643.64   335.3  643.76
   343.2  644.24     353  645.35   362.8  646.27   382.4  647.62   392.2  648.85
     402  650.53   411.8  652.06   421.6  652.71   460.8  652.42   509.9  652.56
#Mann= 3 , 0 , 0
       0     .06       0   320.3    .045       0   335.3     .06       0
Bank Sta=320.3,335.3
XS Rating Curve= 0 ,0
Exp/Cntr=0.3,0.1

Type RM Length L Ch R = 1 ,3328.7  ,265.9,265.5,264
XS GIS Cut Line= 2
     1682860.416      494175.861     1682420.805      494175.034
#Sta/Elev= 30
       0  731.91     9.8  727.49    19.5  722.55    29.3  717.15    48.8  705.58
    87.9  681.28    97.7  675.46   107.5     670   117.2     665   136.8  655.58
   146.5  650.72   156.3  646.21   166.1  643.04   175.8  641.68   180.1  641.46
   195.1  640.84   205.2  640.76   234.5  641.93   293.1  643.72   322.4  644.98
   332.2  645.57   341.9  646.71   361.5  650.62   371.2  652.06     381  652.76
   400.5  653.49   410.3  654.41   420.1  656.92   429.8  660.98   439.6  665.68
#Mann= 3 , 0 , 0
       0      .1       0   180.1    .045       0   195.1     .06       0
Bank Sta=180.1,195.1
XS Rating Curve= 0 ,0
Exp/Cntr=0.3,0.1

Type RM Length L Ch R = 1 ,3063.3  ,335.3,340.6,344.3
XS GIS Cut Line= 2
      1682876.35      493906.165     1682395.496      493926.663
#Sta/Elev= 30
       0  745.76     9.8  741.94    19.6  737.84    29.5  733.39    49.1  723.72
    68.8  713.54    98.2  697.94   147.3   671.5   157.2  665.99     167  660.26
   176.8  654.26   186.6  647.79   196.4  642.03   206.3  639.05   207.4  638.99
   216.1  638.51   222.4  638.67     334  644.02   343.8  644.88   353.6  646.49
   363.4   648.7   373.2  650.56   383.1  651.26   392.9  651.03   402.7  650.56
   412.5  651.17   422.4  653.17   432.2  656.16   471.5  669.53   481.3  673.21
#Mann= 3 , 0 , 0
       0      .1       0   207.4    .045       0   222.4     .06       0
Bank Sta=207.4,222.4
XS Rating Curve= 0 ,0
Exp/Cntr=0.3,0.1

Type RM Length L Ch R = 1 ,2722.7  ,168,166.7,163.5
XS GIS Cut Line= 2
     1683052.785      493648.905     1682348.115      493531.059
#Sta/Elev= 30
       0  796.34    97.9  764.17     137  750.69   176.2  735.66   205.5  723.19
   225.1  713.61   244.7  702.16   264.2  688.86   283.8  673.62   303.4  661.93
     323  652.05   332.8   647.9   352.3   640.7   359.8  639.22   371.9  638.74
   374.8  639.12   391.5   641.7   401.3  642.23   469.8  642.17   508.9  643.45
   528.5  645.29   548.1  648.71   587.2   647.6   606.8  648.34   616.6  649.65
   626.4  652.11   636.2  655.55   694.9  677.86   704.7  682.83   714.5  689.54
#Mann= 3 , 0 , 0
       0      .1       0   359.8    .045       0   374.8     .06       0
Bank Sta=359.8,374.8
XS Rating Curve= 0 ,0
Exp/Cntr=0.3,0.1

Type RM Length L Ch R = 1 ,2556    ,279,278.9,277.8
XS GIS Cut Line= 2
     1683017.893      493449.981     1682277.358      493407.933
#Sta/Elev= 30
       0  775.14    48.8  752.63    68.3  742.62    97.6  724.63   146.4  692.16
   165.9  680.77   175.7   675.7     205  661.83   234.2  650.26   253.8  641.46
   263.5  638.54   270.6  638.21   273.3  638.08   285.6  639.28   302.6  640.66
   400.1  638.94   439.2  639.29   468.5  641.27   478.2   642.5   507.5  648.92
     527  649.73   536.8  651.07   605.1  672.57   624.6  679.72   634.4  685.12
   683.2  719.34   692.9  725.67   702.7  730.64   712.4  734.77   741.7  746.41
#Mann= 3 , 0 , 0
       0      .1       0   270.6    .045       0   285.6     .06       0
Bank Sta=270.6,285.6
XS Rating Curve= 0 ,0
Exp/Cntr=0.3,0.1

Type RM Length L Ch R = 1 ,2277.1  ,254.1,255.2,254.7
XS GIS Cut Line= 2
     1683088.586      493172.808     1682298.171      493150.227
#Sta/Elev= 30
       0  785.36    19.5   779.3      39  772.04    58.6  763.44    78.1   753.2
    87.9  747.55   107.4  735.22   175.7  689.26   185.5  683.18   195.2  677.99
   224.5  666.53   283.1  645.69   292.9  643.22   331.9  637.46   341.7  636.53
     350  636.35   351.4  636.32     365  636.36   527.2  639.52   536.9  640.34
   546.7  642.06   566.2  646.66     576  647.91   585.7  648.34   595.5  649.91
   605.3  653.87     615  659.29   712.6  716.42   722.4  721.62   790.7  753.22
#Mann= 3 , 0 , 0
       0      .1       0     350    .045       0     365     .06       0
Bank Sta=350,365
XS Rating Curve= 0 ,0
Exp/Cntr=0.3,0.1

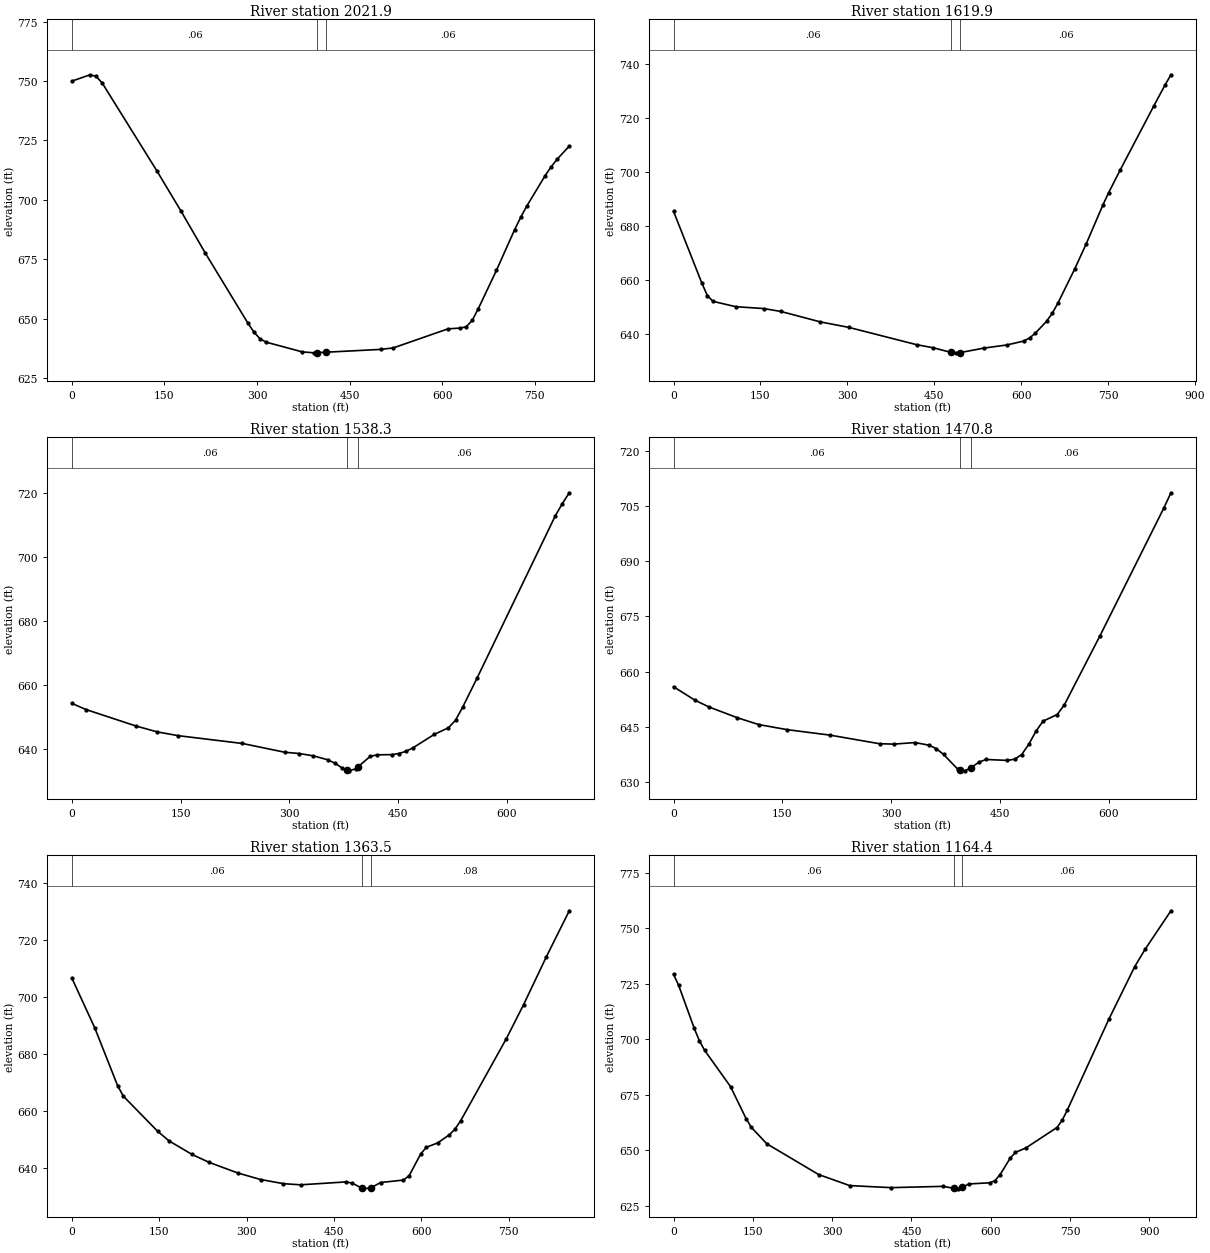
Type RM Length L Ch R = 1 ,2021.9  ,405.3,402,394.7
XS GIS Cut Line= 2
     1683131.447      492925.448     1682326.069      492903.823
#Sta/Elev= 30
       0  749.95    29.5  752.62    39.3  751.96    49.1  749.18   137.6  712.27
   176.8  695.32   216.2  677.65   284.9  648.33   294.8   644.5   304.6   641.7
   314.4  640.25   373.4  636.13     393  635.74   397.2   635.8   412.2  636.01
   501.1   637.2   520.7  637.82   609.2  645.82   628.8  646.16   638.6  646.67
   648.5  649.38   658.3  654.28   687.8  670.44   717.2  687.53   727.1  692.74
   736.9  697.43   766.4  710.15   776.2  713.89     786  717.12   805.7  722.64
#Mann= 3 , 0 , 0
       0     .06       0   397.2    .045       0   412.2     .06       0
Bank Sta=397.2,412.2
XS Rating Curve= 0 ,0
Exp/Cntr=0.3,0.1

Type RM Length L Ch R = 1 ,1619.9  ,81.7,81.6,80.9
XS GIS Cut Line= 2
     1683126.037      492469.698      1682286.67      492648.883
#Sta/Elev= 30
       0  685.48    48.8  658.85    58.5  654.12    68.3  652.02   107.3  650.05
     156  649.35   185.3  648.27   253.6  644.39   302.4  642.37   419.4  635.94
   448.6  634.77   479.3  633.04   487.7  632.91   494.3  632.99   536.4   634.7
   575.4  635.84   604.7  637.31   614.4  638.45   624.2  640.18   643.7  644.64
   653.5  647.59   663.2  651.34   692.5  664.17     712  673.34   741.2  687.97
     751  692.45   770.5  700.71     829  724.71   848.5  732.53   858.3  736.17
#Mann= 3 , 0 , 0
       0     .06       0   479.3    .045       0   494.3     .06       0
Bank Sta=479.3,494.3
XS Rating Curve= 0 ,0
Exp/Cntr=0.3,0.1

Type RM Length L Ch R = 1 ,1538.3  ,67.7,67.5,67.7
XS GIS Cut Line= 2
     1682990.666      492429.142     1682316.608      492555.878
#Sta/Elev= 30
       0  654.23    19.6  652.31    88.2  647.18   117.6  645.33     147  644.13
   235.2   641.7   293.9  638.94   313.5  638.56   333.1  637.82   352.7  636.61
   362.5  635.56   372.3   634.1   379.5  633.39   382.1  633.14   391.9  633.81
   394.5  634.37   411.5  637.69   421.3  638.15   440.9  638.21   450.7  638.55
   460.5  639.22   470.3  640.32   499.7  644.53   519.3  646.62   529.1  648.99
   538.9  653.05   558.5  662.04   666.3  712.76   676.1  716.66   685.9  720.12
#Mann= 3 , 0 , 0
       0     .06       0   379.5    .045       0   394.5     .06       0
Bank Sta=379.5,394.5
XS Rating Curve= 0 ,0
Exp/Cntr=0.3,0.1

Type RM Length L Ch R = 1 ,1470.8  ,112.1,107.4,102.5
XS GIS Cut Line= 2
     1682978.539       492364.64     1682304.481      492491.376
#Sta/Elev= 30
       0  655.87    29.4  652.22      49  650.35    88.2  647.42   117.6  645.57
   156.8  644.19   215.6  642.71   284.2  640.36   303.7  640.26   333.1  640.68
   352.7  639.95   362.5  638.99   372.3  637.47   391.9  633.45   395.3  633.29
   401.7  632.99   410.3  633.84   421.3  635.38   431.1  636.08   460.5  635.83
   470.3  636.15   480.1  637.42   489.9  640.21   499.7  643.74   509.5   646.5
   529.1  648.31   538.9  650.93   587.9  669.66   676.1  704.47   685.9  708.62
#Mann= 3 , 0 , 0
       0     .06       0   395.3    .045       0   410.3     .06       0
Bank Sta=395.3,410.3
XS Rating Curve= 0 ,0
Exp/Cntr=0.3,0.1

Type RM Length L Ch R = 1 ,1363.5  ,198.7,199.1,199.2
XS GIS Cut Line= 2
     1683009.824      492144.969     1682221.326       492473.51
#Sta/Elev= 30
       0  706.65    39.3  689.22    78.6  668.96    88.4  665.29   147.3     653
   166.9  649.62   206.2   644.9   235.6  642.11   284.7   638.4     324   636.1
   363.3  634.64   392.7  634.24   471.3  635.26   481.1  634.85   498.6  633.03
   500.7  632.83   513.6  633.18   530.2  635.05   569.5   635.9   579.3  637.46
   598.9     645   608.7  647.37   628.4  648.94     648  651.72   657.8  653.71
   667.7  656.68   746.2  685.46   775.7  697.32   814.9  714.13   854.2  730.22
#Mann= 3 , 0 , 0
       0     .06       0   498.6    .045       0   513.6     .08       0
Bank Sta=498.6,513.6
XS Rating Curve= 0 ,0
Exp/Cntr=0.3,0.1

Type RM Length L Ch R = 1 ,1164.4  ,1171.8,1164.4,1144.7
XS GIS Cut Line= 2
     1682977.466      491951.083     1682104.372      492301.525
#Sta/Elev= 30
       0  729.29     9.8  724.24    39.2  704.94      49  699.31    58.8  695.05
   107.8  678.71   137.2  664.34     147  660.41   176.4  652.98   274.4  639.12
   333.2  634.14   411.6  633.22   509.6   633.8   531.1  632.89     539  632.68
   546.1  633.38   558.6  634.88   597.8  635.39   607.6   636.3   617.4  638.97
     637  646.57   646.8  649.09   666.4  651.09   725.2  660.29     735   663.5
   744.8  668.15   823.2  708.96   872.2  732.67   891.8  740.47   940.8  757.86
#Mann= 3 , 0 , 0
       0     .06       0   531.1    .045       0   546.1     .06       0
Bank Sta=531.1,546.1
XS Rating Curve= 0 ,0
Exp/Cntr=0.3,0.1

Chan Stop Cuts=-1
Use User Specified Reach Order=0
Composite Channel Slope=5